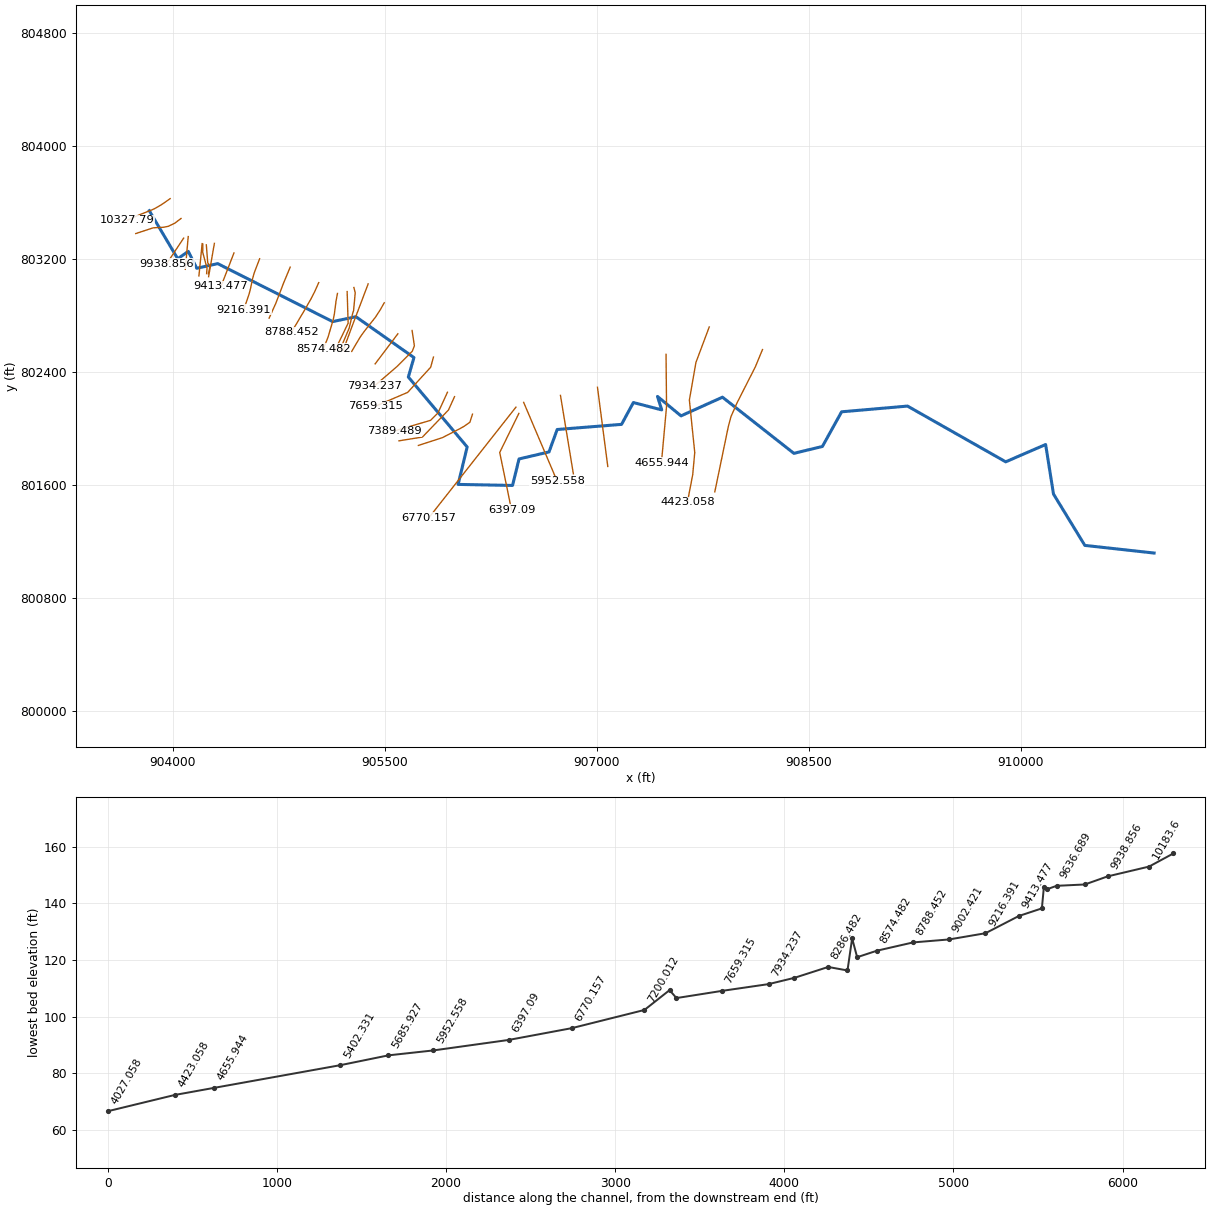
--- 13111_ras.prj (project) ---

Proj Title=13111
Current Plan=p01
Default Exp/Contr=0.3,0.1
English Units
Geom File=g01
Flow File=f01
Plan File=p01
Y Axis Title=Elevation
X Axis Title(PF)=Main Channel Distance
X Axis Title(XS)=Station
BEGIN DESCRIPTION:
RFD model 13111 exported to HEC-RAS
END DESCRIPTION:

--- 13111_ras.p01 (plan) ---

Plan Title=Plan 01
Program Version=4.10
Short Identifier=Plan 01
Geom File=g01
Flow File=f01
Subcritical Flow
Calc Critical at every XS
Secant Critical Depth

--- 13111_ras.f01 (steady flow) ---

Flow Title=Flow 01
Program Version=5.01
Number of Profiles= 6
Profile Names=10yr,25yr,50yr,100yr,100plus,500yr
River Rch & RM=13111,31,10327.79
  431.96  657.63  860.11 1031.82 1506.46 2174.01
River Rch & RM=13111,31, 10183.6
  435.11  662.54  866.65 1039.78 1518.08 2188.89
River Rch & RM=13111,31,9938.856
  452.99  690.51  903.91 1085.15 1584.32 2273.71
River Rch & RM=13111,31,9803.899
   456.1  695.38  910.38 1093.03 1595.82 2288.33
River Rch & RM=13111,31,9636.689
  457.26  697.19   912.8 1095.97 1600.11  2293.8
River Rch & RM=13111,31,9561.837
  475.77   725.8   950.6 1141.68 1666.85 2377.11
River Rch & RM=13111,31,9413.477
  478.45  729.99  956.18 1148.48 1676.78 2389.69
River Rch & RM=13111,31,9216.391
  484.18  738.95  968.13 1163.02 1698.02 2416.55
River Rch & RM=13111,31,9002.421
  501.97  766.82 1005.28  1208.3 1764.12 2499.97
River Rch & RM=13111,31,8788.452
  517.86  791.83 1038.72 1249.15 1823.76 2575.35
River Rch & RM=13111,31,8574.482
  522.57  799.27  1048.7 1261.37  1841.6 2597.97
River Rch & RM=13111,31,8457.708
  523.29  800.41 1050.23 1263.25 1844.35 2601.44
River Rch & RM=13111,31,8286.482
   537.9  823.42 1081.01 1300.88 1899.28 2670.52
River Rch & RM=13111,31,8086.741
  549.02  840.99 1104.58 1329.74 1941.42 2723.57
River Rch & RM=13111,31,7934.237
   555.1   850.6 1117.46 1345.52 1964.46  2752.5
River Rch & RM=13111,31,7659.315
  593.82  911.59  1199.1 1445.32 2110.17 2933.55
River Rch & RM=13111,31,7389.489
  597.28  917.09 1206.49  1454.4 2123.42  2950.1
River Rch & RM=13111,31,7348.531
  600.03  921.46 1212.38 1461.63 2133.98  2963.3
River Rch & RM=13111,31,7200.012
  602.76  925.81 1218.24 1468.84 2144.51 2976.49
River Rch & RM=13111,31,6770.157
  606.16  931.24 1225.55 1477.84 2157.65 2992.93
River Rch & RM=13111,31, 6397.09
  941.65 1464.81 1944.31 2361.36 3447.58 4545.72
River Rch & RM=13111,31,5952.558
  960.52 1494.85 1984.79 2411.15 3520.28 4630.46
River Rch & RM=13111,31,5685.927
  965.76 1503.18 1996.03 2424.98 3540.47 4653.96
River Rch & RM=13111,31,5402.331
  977.43 1521.78 2021.11 2455.83 3585.51 4706.34
River Rch & RM=13111,31,4655.944
  983.88 1532.03 2034.94 2472.84 3610.35 4735.19
Boundary for River Rch & Prof#=13111,31,1
Up Type= 0
Dn Type= 2
Boundary for River Rch & Prof#=13111,31,2
Up Type= 0
Dn Type= 2
Boundary for River Rch & Prof#=13111,31,2
Up Type= 0
Dn Type= 2
Boundary for River Rch & Prof#=13111,31,2
Up Type= 0
Dn Type= 2
Boundary for River Rch & Prof#=13111,31,2
Up Type= 0
Dn Type= 2
Boundary for River Rch & Prof#=13111,31,2
Up Type= 0
Dn Type= 2

--- 13111_ras.g01 (geometry) ---

Geom Title=13111
Program Version=4.10

River Reach=13111,31
Reach XY= 30
903834.197004233803540.650005246904034.934851441803201.023269119
904109.804643154803253.106602462904169.483462544803133.748963571
904317.667686613803166.712188086905130.738717113802756.567749524
905295.459525976802790.939994325905705.941795916802502.238546906
905666.383032622802364.275825611906082.460893124801869.643060773
906018.441795887801604.886116334906403.342758447801597.459032927
 906449.43889031801784.874748967906661.499564082801834.636869686
906719.322806659801993.312458422907174.519931497802029.514819189
907258.276865334802184.029634868907458.797698679802131.946301554
907428.849782022802226.998384855907595.000570537802089.671320749
907888.485198707802221.790051549908393.693532024801824.654634876
 908595.32298276801873.205194314908731.333815875802118.530043383
909197.470689746802158.866467711909892.012916986801764.683864445
910174.473053994801887.117245889910230.100003302801536.441488318
910451.876894597801173.344169995910941.505751135801119.393252681

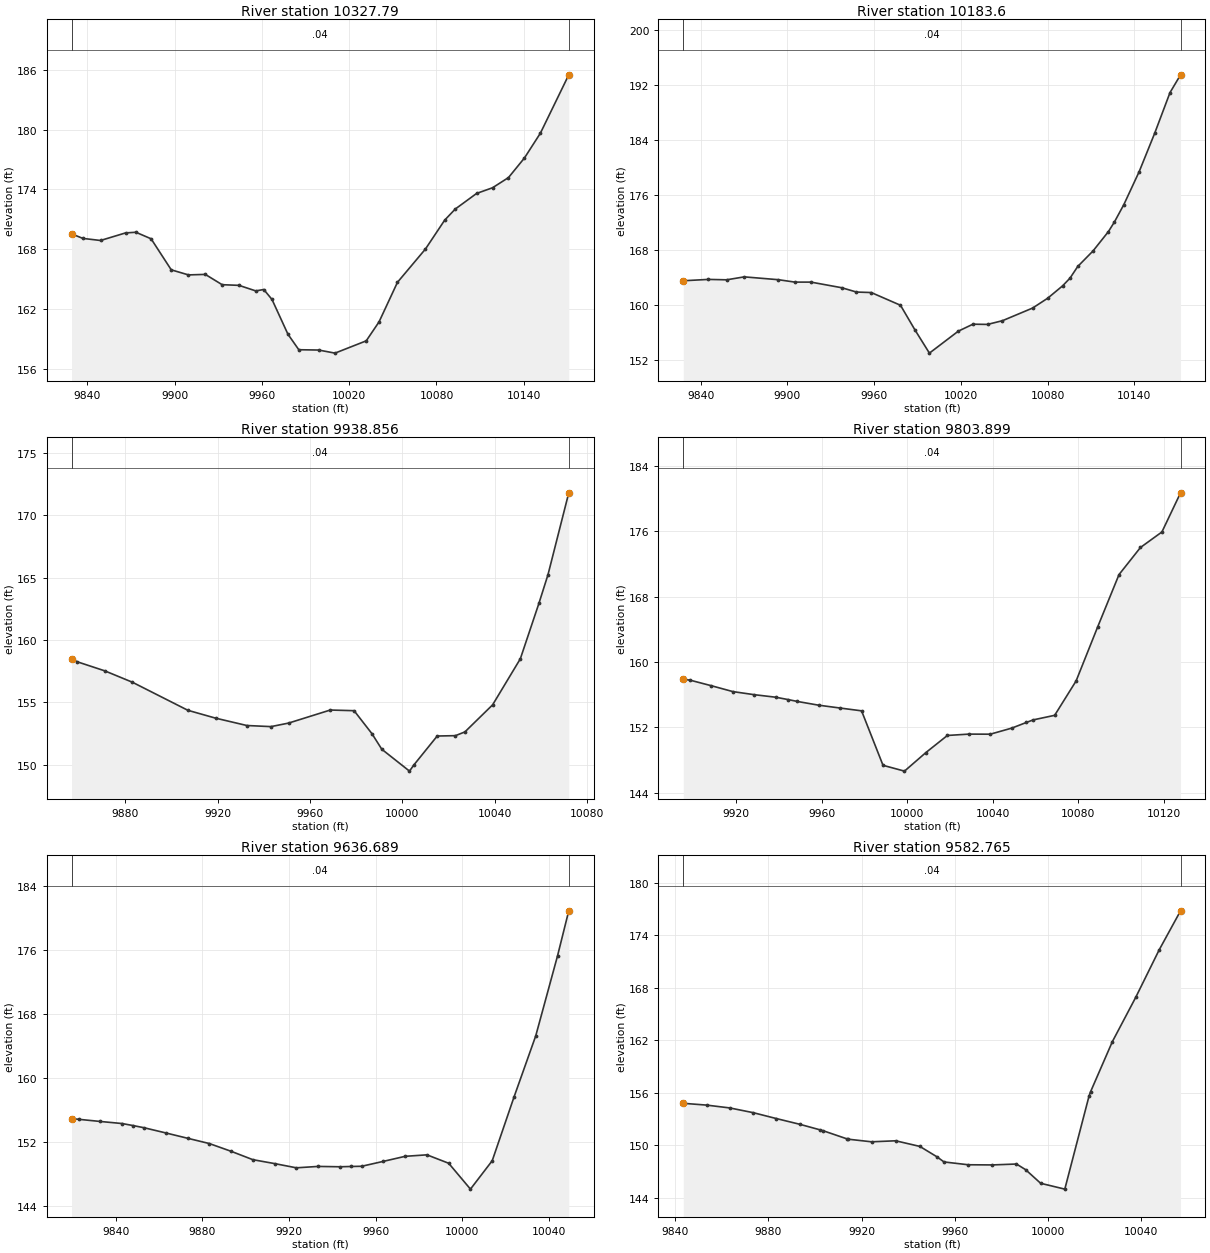
Type RM Length L Ch R = 1 ,10327.79,144.190100,144.190100,144.190100
XS GIS Cut Line= 6
903981.391834956803626.124021217903920.202150658803583.792416559
903872.644878359803556.141846608903847.528536984803544.686463943
903767.063046273803513.401780832903677.194280313803472.978965727
#Sta/Elev= 30
9829.066169.54819836.838169.08839848.998168.87889866.195169.63699873.317 169.704
9883.772169.04879897.637165.93599909.489165.42829921.056165.47939932.623164.4473
9944.191 164.3819955.758163.82399961.234163.96479966.885162.97239977.876159.4811
9985.332157.9278    9999 157.89710010.23157.5873 10031.7158.818910040.52160.7224
10053.17164.685810072.42168.023510085.65  170.92 10092.9 172.02910107.58173.5943
10118.54174.163510129.51175.184210140.47177.146910151.44179.633510170.96185.4843
#Mann= 3 , 0 , 0
9829.066    0.04       09829.066    0.04       010170.96    0.04       0
#XS Ineff= 2 , 0
       0                               0
Bank Sta=9829.066,10170.96
Exp/Cntr=0.3,0.1

Type RM Length L Ch R = 1 , 10183.6,244.739600,244.739600,244.739600
XS GIS Cut Line= 6
904058.211183692803485.963915449904013.783737427 803452.27333286
903968.525165528803430.850368009903934.607072537803423.767186267
903862.047442096803420.081109618903738.155521414803379.256730631
#Sta/Elev= 30
9828.052163.48779845.407163.68589857.995163.62649870.234164.05599893.844163.6419
9905.218163.29269916.358163.29199937.627162.47269947.842161.84249958.058 161.771
9978.284159.91649988.285156.32299998.287152.939410018.29156.1434 10028.4157.1576
10038.51157.125710048.83 157.66710069.66159.507810080.07160.938110090.48162.7581
10095.57163.879410100.89165.570110111.47 167.83510122.12170.657310126.24172.0478
10132.77174.584410143.42179.409810154.07184.966810164.72190.921510172.01193.5072
#Mann= 3 , 0 , 0
9828.052    0.04       09828.052    0.04       010172.01    0.04       0
#XS Ineff= 2 , 0
       0                               0
Bank Sta=9828.052,10172.01
Exp/Cntr=0.3,0.1

Type RM Length L Ch R = 1 ,9938.856,134.957100,134.957100,134.957100
XS GIS Cut Line= 2
904077.018983359803346.992793195903957.839176497803167.513679289
#Sta/Elev= 23
9856.623158.51189859.016158.26019871.019157.52879883.023 156.6139907.031154.3644
9919.035 153.7359932.582153.14429943.043153.0553 9950.66153.33849968.737154.3857
9979.055154.33279986.814152.48279991.058151.240510003.06149.485810004.89 149.967
10015.07152.301310022.97152.330210027.07152.631610039.07154.801610051.08158.4933
10059.12162.931210063.08165.248710072.07171.8053
#Mann= 3 , 0 , 0
9856.623    0.04       09856.623    0.04       010072.07    0.04       0
#XS Ineff= 2 , 0
       0                               0
Bank Sta=9856.623,10072.07
Exp/Cntr=0.3,0.1

Type RM Length L Ch R = 1 ,9803.899,167.210300,167.210300,167.210300
XS GIS Cut Line= 2
904109.376260183 803358.08881699904088.542926849803126.317983657
#Sta/Elev= 27
 9895.21157.87759898.311157.78389908.352157.09519918.392 156.3789928.432155.9977
9938.473155.68779944.092155.40769948.513155.17299958.553154.71089968.594154.3619
9978.634154.01929988.674147.34369998.715 146.63110008.75148.9085 10018.8151.0022
10028.84151.166910038.88151.158510048.92151.902210055.79152.597810058.96152.9102
   10069153.469210079.04157.683810089.08164.269810099.12 170.71810109.16174.0372
 10119.2175.939710127.92180.7353
#Mann= 3 , 0 , 0
 9895.21    0.04       0 9895.21    0.04       010127.92    0.04       0
#XS Ineff= 2 , 0
       0                               0
Bank Sta=9895.21,10127.92
Exp/Cntr=0.3,0.1

Type RM Length L Ch R = 1 ,9636.689,53.924300,53.924300,53.924300
XS GIS Cut Line= 2
904207.841666977803308.307794171904184.993855767803079.829682073
#Sta/Elev= 28
9819.629154.95639822.953154.87119833.003154.59939843.053154.34139848.187154.0837
9853.103153.82059863.153153.17129873.203152.50719883.252151.84649893.302150.8807
9903.352149.83249913.402149.34459923.452148.81639933.502  148.999943.552148.9464
9948.686148.98249953.602 149.0089963.651149.62349973.701150.25129983.751150.4363
9993.801149.384710003.85146.1558 10013.9149.700110023.95157.6398   10034165.2896
10044.05175.263310049.18180.825610049.25 180.895
#Mann= 3 , 0 , 0
9819.629    0.04       09819.629    0.04       010049.25    0.04       0
#XS Ineff= 2 , 0
       0                               0
Bank Sta=9819.629,10049.25
Exp/Cntr=0.3,0.1

Type RM Length L Ch R = 1 ,9582.765,20.927500,20.927500,20.927500
XS GIS Cut Line= 4
 904212.30706954 803304.96524255904211.774941564803246.431165949
904242.330322474803134.358337805 904239.44559598803095.838950738
#Sta/Elev= 27
 9843.49154.80479853.455   154.69863.456154.27459873.456153.73569883.457153.0578
9893.457152.40639902.026151.7795 9903.51151.66619913.875150.72349914.287150.6996
 9924.24150.40289934.605150.5187 9944.97149.87559952.304 148.6889955.335148.1003
  9965.7147.77749976.065147.7581 9986.43 147.8629990.322147.21999996.795145.6594
10007.16144.991110017.52 155.59510018.19156.112110027.57161.8591 10037.6166.9274
10047.63172.341410056.82176.8145
#Mann= 3 , 0 , 0
 9843.49    0.04       0 9843.49    0.04       010056.82    0.04       0
#XS Ineff= 2 , 0
       0                               0
Bank Sta=9843.49,10056.82
Exp/Cntr=0.3,0.1

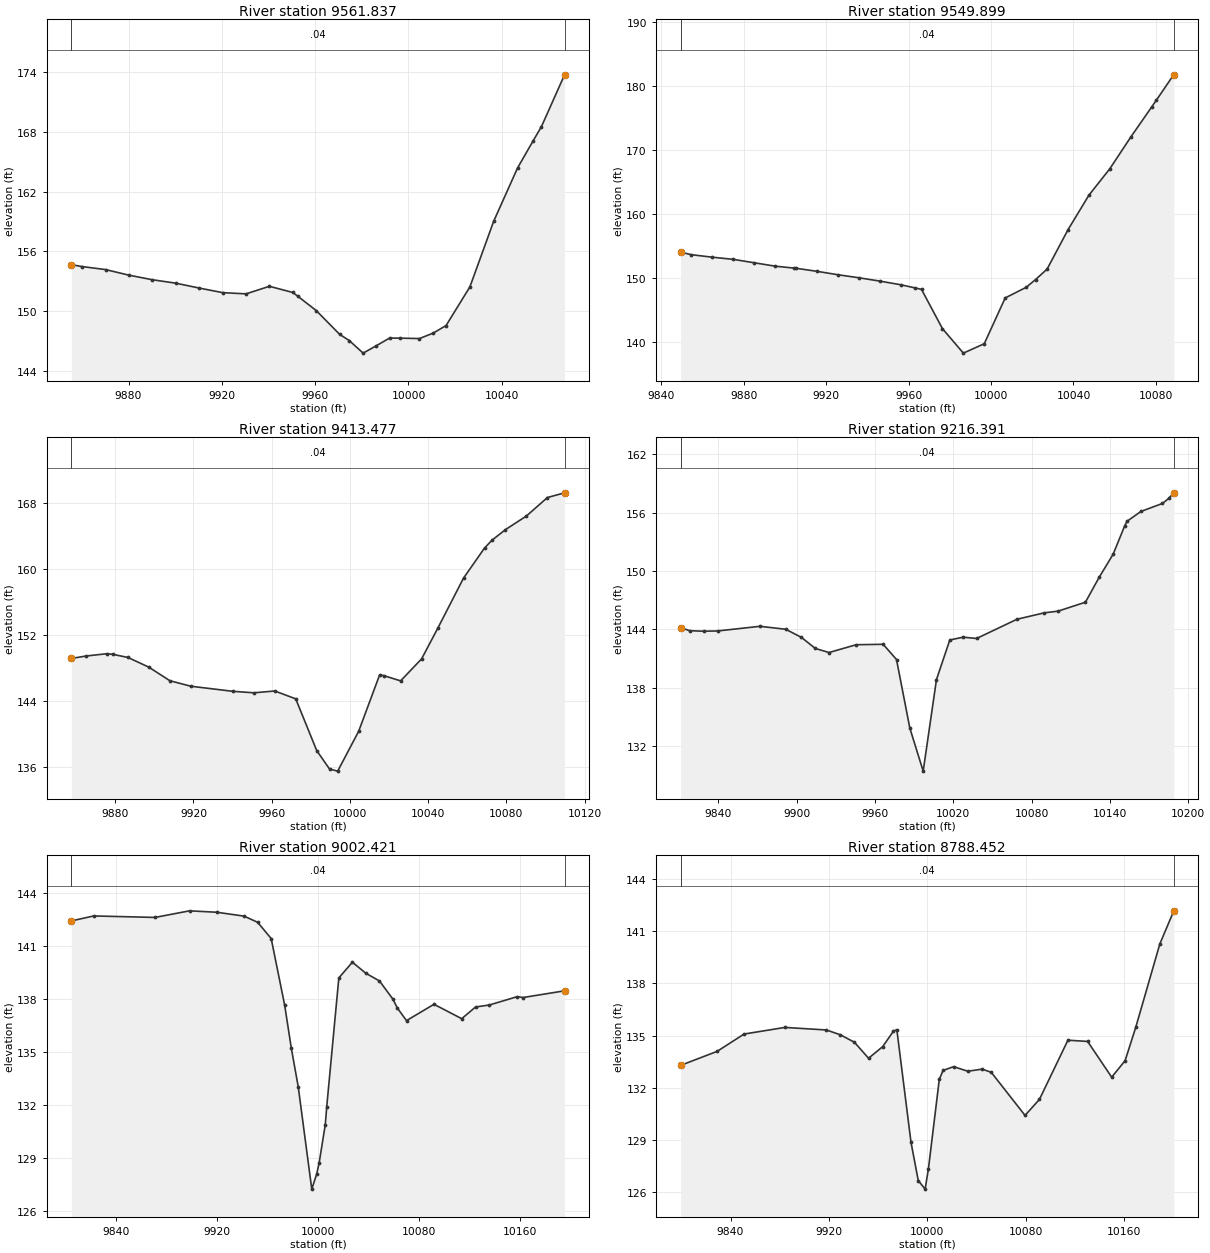
Type RM Length L Ch R = 1 ,9561.837,11.938500,11.938500,11.938500
XS GIS Cut Line= 5
904237.317084104 803299.64396286904246.734214157803180.882210076
904248.438046962 803169.61798197904263.772542387803150.402534023
904252.216667235803095.306822762
#Sta/Elev= 28
9855.491154.6643 9860.15154.47279870.181154.17239880.212153.60879890.244153.1508
9900.275152.80599910.307152.31579920.338151.85559930.369151.73229940.401152.4918
9950.432151.87149952.686151.47089960.463150.05559970.495147.66619974.626147.0408
9980.575145.77789986.018146.49299991.926147.29589996.538147.282410004.72147.2412
 10010.6147.790610016.12148.546810026.34152.436310036.56159.043810046.77164.3865
10053.34167.066410056.99168.5287 10066.9173.7397
#Mann= 3 , 0 , 0
9855.491    0.04       09855.491    0.04       0 10066.9    0.04       0
#XS Ineff= 2 , 0
       0                               0
Bank Sta=9855.491,10066.9
Exp/Cntr=0.3,0.1

Type RM Length L Ch R = 1 ,9549.899,136.421500,136.421500,136.421500
XS GIS Cut Line= 2
904294.422846298 803310.11156874904253.537289397803074.418358365
#Sta/Elev= 30
9849.451153.98929854.639153.59419864.788153.20259874.938152.86569885.087152.3332
9895.236   151.89904.582 151.4929905.386 151.4719915.535150.99479925.684150.4596
9935.834149.98829945.983149.46919956.132148.8963 9963.09148.40129966.282148.1696
9976.431142.0332 9986.58138.1992 9996.73139.673110006.88146.834710017.03148.4849
 10021.6149.705610027.18151.330810037.33157.492410047.48162.898810057.63167.0393
10067.78171.987510077.92176.693110080.11177.714310088.07181.481810088.66181.7199
#Mann= 3 , 0 , 0
9849.451    0.04       09849.451    0.04       010088.66    0.04       0
#XS Ineff= 2 , 0
       0                               0
Bank Sta=9849.451,10088.66
Exp/Cntr=0.3,0.1

Type RM Length L Ch R = 1 ,9413.477,197.086500,197.086500,197.086500
XS GIS Cut Line= 2
904432.694785399803241.992360662904341.590685506803006.845292018
#Sta/Elev= 28
9857.539149.15319865.037149.44999875.762149.72929878.838149.64899886.486149.2767
 9897.21148.09539907.935146.45539918.659145.78999940.108145.17489950.832144.9941
9961.556145.2124 9972.28 144.2629983.005137.99799989.559135.76219993.729135.5056
10004.45140.328810015.18147.163310017.24 147.079 10025.9146.439810036.63149.1018
10044.92152.822910058.07 158.887 10068.8 162.525 10072.6163.473810079.52164.7621
10090.25166.414910100.97 168.64910109.72169.2192
#Mann= 3 , 0 , 0
9857.539    0.04       09857.539    0.04       010109.72    0.04       0
#XS Ineff= 2 , 0
       0                               0
Bank Sta=9857.539,10109.72
Exp/Cntr=0.3,0.1

Type RM Length L Ch R = 1 ,9216.391,213.969500,213.969500,213.969500
XS GIS Cut Line= 6
904614.425170339803201.332891497904575.590433723803099.544599945
904564.184668059 803058.99407253904550.794405962802993.846781914
904539.809762242802951.128278831904502.010139368802841.322473064
#Sta/Elev= 30
9811.066144.1992  9817.9143.87259828.691143.81749839.482143.84639871.856144.3242
9891.655144.01699903.659143.18169914.258142.04719924.762141.62819945.538142.4294
9966.247142.47439976.467140.90949986.688133.85359996.909129.4362 10007.1138.8512
 10017.3142.9147 10027.5143.207410037.81143.071810068.79145.048810089.72145.7086
10100.22145.881610121.21146.799810131.76149.366310142.42151.726410151.22 154.623
10153.07 155.11910163.72156.130210180.26156.953510185.02157.470610188.94 158.045
#Mann= 3 , 0 , 0
9811.066    0.04       09811.066    0.04       010188.94    0.04       0
#XS Ineff= 2 , 0
       0                               0
Bank Sta=9811.066,10188.94
Exp/Cntr=0.3,0.1

Type RM Length L Ch R = 1 ,9002.421,213.969600,213.969600,213.969600
XS GIS Cut Line= 6
904830.470159508803141.340298049904783.434324759803028.458077148
904757.851083907802961.377239171904757.137347672802959.508929617
904728.876154498802885.770983081904681.496196725802780.872573123
#Sta/Elev= 30
9804.917142.41739822.619142.69969871.137142.61559898.452142.98899920.119142.9074
 9941.61142.68829952.312142.33939963.015141.42369973.718137.64129978.938135.2249
 9984.42133.03599995.123127.2528    9999 128.105   10001128.753310005.83130.9057
10006.97131.922210016.54139.196810027.25140.082710037.96139.455610048.67139.0238
10059.38137.987910062.86137.485310070.08136.781310091.79137.704810113.73136.8906
10124.71137.552110135.68137.665310157.62138.135510162.27138.086810195.07138.4661
#Mann= 3 , 0 , 0
9804.917    0.04       09804.917    0.04       010195.07    0.04       0
#XS Ineff= 2 , 0
       0                10031.46       0
Bank Sta=9804.917,10195.07
Exp/Cntr=0.3,0.1

Type RM Length L Ch R = 1 ,8788.452,213.969500,213.969500,213.969500
XS GIS Cut Line= 6
905032.352706128  803032.0967004905002.730411137802966.049060015
904977.344072297 802916.82092607904940.912088687802852.647072982
904933.826425521802840.336432925904839.203275735802680.939185777
#Sta/Elev= 30
9799.431 133.2929829.128 134.0969851.048135.08999884.249135.46959918.003135.3231
  9929.3135.04869940.799134.61889952.298133.70039963.798134.37039972.463135.2471
9975.297135.33919986.796128.88349992.717126.68349998.295 126.192   10001127.3689
10009.82132.488110012.85132.999610021.41133.218210033.04132.956210044.67133.0774
10052.09132.893310079.56130.421710091.27131.339610114.44134.737210130.45134.6654
10150.04132.614110160.96 133.56610169.63135.480710189.22140.266510200.57142.1595
#Mann= 3 , 0 , 0
9799.431    0.04       09799.431    0.04       010200.57    0.04       0
#XS Ineff= 2 , 0
       0                10032.75       0
Bank Sta=9799.431,10200.57
Exp/Cntr=0.3,0.1

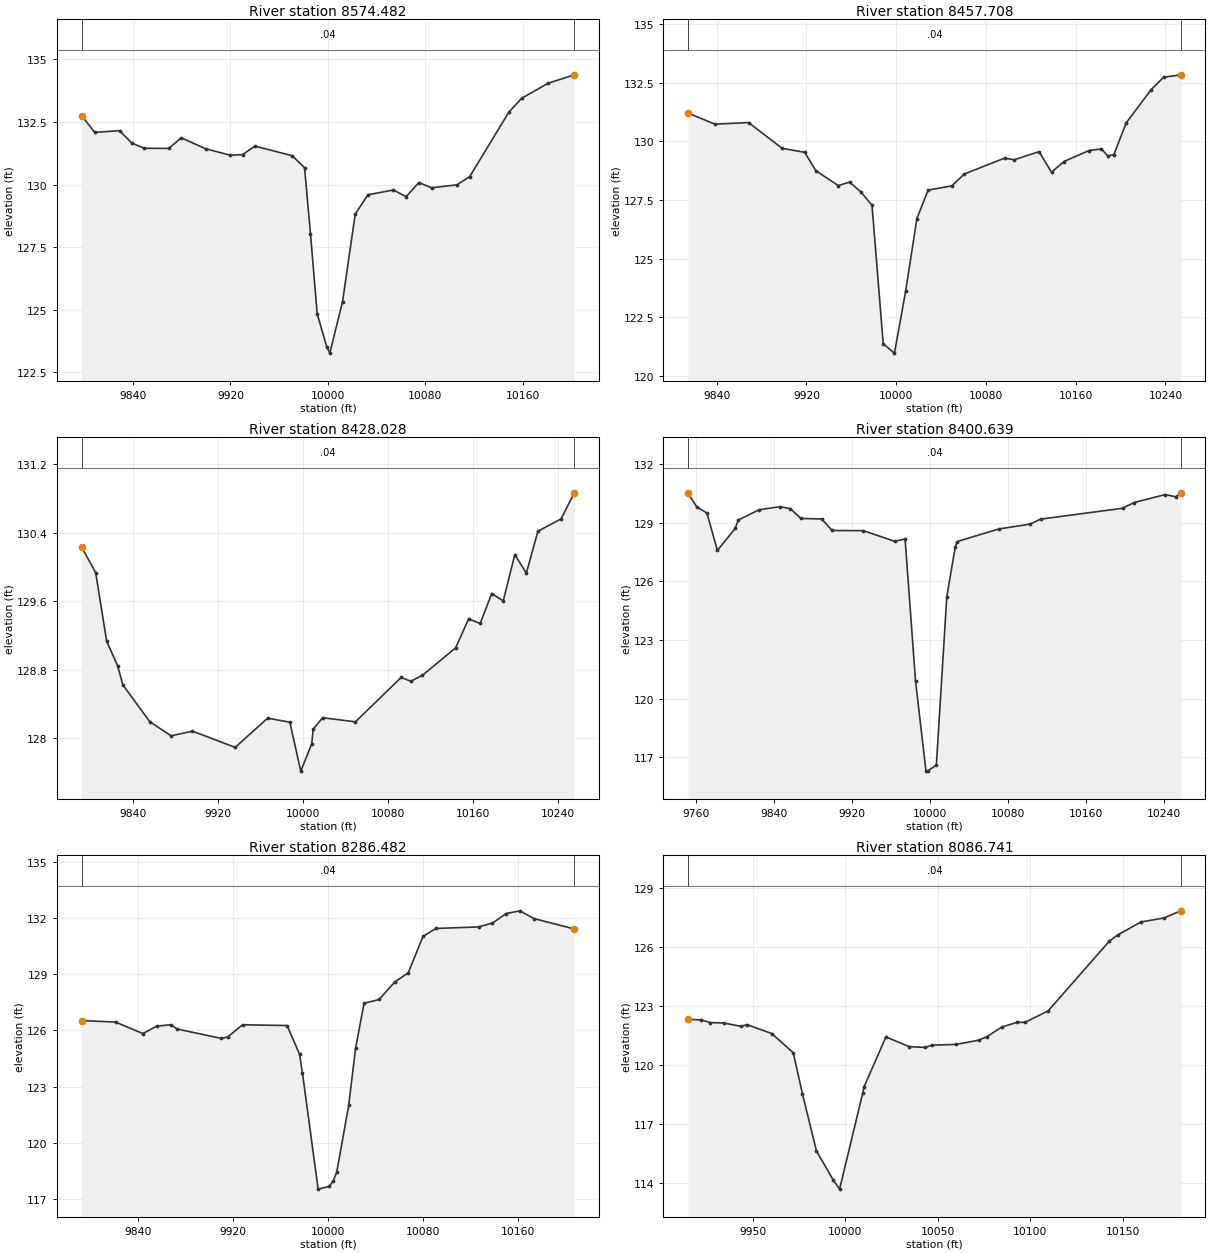
Type RM Length L Ch R = 1 ,8574.482,116.774300,116.774300,116.774300
XS GIS Cut Line= 6
905164.983049347802955.614660292905154.986890866802902.254237399
905143.068873036802810.040728862905136.041448498802773.983610852
905098.203547155 802646.24294224905066.288819131 802565.16407499
#Sta/Elev= 30
9797.809132.75819808.609132.08579828.957132.1574 9839.13131.65679849.304131.4516
9869.496 131.4489879.579 131.8699899.745131.43089919.912131.17369929.995131.2007
9940.078131.5385 9970.59131.15599980.778130.67759985.664128.03739991.146124.8431
    9999123.523910001.52123.267710011.96 125.32410022.39128.827210032.83129.5949
10053.71 129.78510064.15 129.51910074.59130.081910085.03129.8741 10105.9129.9909
10116.37130.323310148.27 132.88410159.03133.4519 10180.7134.0506 10202.2134.3863
#Mann= 3 , 0 , 0
9797.809    0.04       09797.809    0.04       0 10202.2    0.04       0
#XS Ineff= 2 , 0
       0                               0
Bank Sta=9797.809,10202.2
Exp/Cntr=0.3,0.1

Type RM Length L Ch R = 1 ,8457.708,29.680200,29.680200,29.680200
XS GIS Cut Line= 3
905233.508204627802968.982914212905240.553047732802745.560747177
905146.702649072802551.231178101
#Sta/Elev= 30
 9814.35131.20219838.345130.7274 9868.36 130.7969898.374129.69699918.384129.5304
9928.389128.74389948.399128.11099958.404128.26269968.409127.84639978.414 127.278
9988.419121.37549998.424120.977810008.43 123.62410018.43126.705210028.44127.9195
10049.61128.102210060.72128.605410096.64129.283410105.14129.210210127.35 129.558
10138.45128.682610149.56129.137710171.77129.602510182.87 129.67310188.62129.3818
10193.98129.425210205.08130.784810227.29132.1992 10238.4132.725510253.69132.8287
#Mann= 3 , 0 , 0
 9814.35    0.04       0 9814.35    0.04       010253.69    0.04       0
#XS Ineff= 2 , 0
       09874.402        10085.66       0
Bank Sta=9814.35,10253.69
Exp/Cntr=0.3,0.1

Type RM Length L Ch R = 1 ,8428.028,27.388600,27.388600,27.388600
XS GIS Cut Line= 6
905281.141369332802997.904761843905290.604910485 802960.23566844
905279.081121294802834.434303101905271.485635183802810.562775323
905247.614107405 802709.65131699905181.424871294 802553.40131699
#Sta/Elev= 29
9791.806130.23279805.112129.93229815.423129.13299825.733128.84749830.646128.6241
9855.987128.19399876.071128.02989896.155128.08439936.322 127.8959966.874128.2356
9987.746128.18869998.032127.617910008.32127.934810009.73128.1069 10018.6 128.241
10049.44128.192610092.42128.710310101.63128.666710112.49128.7355 10143.7129.0555
10155.94129.3937 10166.8129.339910177.66129.688410188.52129.603410199.38130.1434
10210.24129.9269 10221.1130.415510242.82130.559310255.41130.8637
#Mann= 3 , 0 , 0
9791.806    0.04       09791.806    0.04       010255.41    0.04       0
#XS Ineff= 2 , 0
       09931.851        10074.77       0
Bank Sta=9791.806,10255.41
Exp/Cntr=0.3,0.1

Type RM Length L Ch R = 1 ,8400.639,114.156900,114.156900,114.156900
XS GIS Cut Line= 3
905382.162718516803023.236386434905268.230426849802722.672150323
905204.211329627802550.146108657
#Sta/Elev= 30
9751.673130.49759760.481129.81919771.176129.4807 9781.87127.57699800.094128.6988
9803.259129.12719824.647129.65519846.036129.8098 9856.73129.71159867.425129.2098
9888.813129.18279899.508128.59569931.591128.58629963.674128.04349974.368128.1619
9985.062  120.929995.757116.31999997.582116.303410006.45116.619410017.15125.2115
 10025.8127.743910027.84 128.03210070.62128.674710102.62  128.9210113.29129.1752
10197.37129.730210209.29130.024810241.28130.431310251.95130.315310257.13 130.519
#Mann= 3 , 0 , 0
9751.673    0.04       09751.673    0.04       010257.13    0.04       0
#XS Ineff= 2 , 0
       09890.866                       0
Bank Sta=9751.673,10257.13
Exp/Cntr=0.3,0.1

Type RM Length L Ch R = 1 ,8286.482,199.741100,199.741100,199.741100
XS GIS Cut Line= 6
905496.026004964802889.802017718905465.630435765802836.767692794
905432.610754585802786.195515993905355.769277717802689.184581176
905326.541272079802648.593608099905265.629039463802545.656965441
#Sta/Elev= 30
9792.523126.5267 9821.11126.44519844.162125.83229855.762126.22859867.705126.3021
9873.095126.07499909.678125.58169915.543125.64359928.046 126.3029965.559126.2612
9976.047124.73619978.539123.7117 9991.73117.5345   10001117.680710004.53117.9817
 10007.4118.445310017.43121.997910023.23125.041510030.33 127.44510042.99127.6504
10056.27128.582610067.64129.077110079.96131.012610090.88131.439410126.89131.5215
10138.51131.727310150.13 132.23710161.75132.379710173.37131.967510207.46131.4112
#Mann= 3 , 0 , 0
9792.523    0.04       09792.523    0.04       010207.46    0.04       0
#XS Ineff= 2 , 0
       0 9936.02                       0
Bank Sta=9792.523,10207.46
Exp/Cntr=0.3,0.1

Type RM Length L Ch R = 1 ,8086.741,152.504500,152.504500,152.504500
XS GIS Cut Line= 2
905592.314245934802670.439150198905431.723968156802457.765539087
#Sta/Elev= 30
9914.873122.33329921.689122.30859927.011122.17169934.219122.14879943.605121.9781
 9946.75122.0661  9960.2121.61299971.811120.63859976.795118.54519984.342115.6493
9993.389114.16949996.873113.7008 10009.4118.593610009.98118.878710021.93121.4424
10034.46120.947410043.17120.9065   10047121.024310059.77121.059510072.06121.2739
10076.36121.444210084.59121.942610092.96122.187310097.12 122.18110109.65122.7656
10142.74126.313410147.24126.621810159.77 127.286 10172.3127.492310181.37127.8542
#Mann= 3 , 0 , 0
9914.873    0.04       09914.873    0.04       010181.37    0.04       0
#XS Ineff= 2 , 0
       09935.248                       0
Bank Sta=9914.873,10181.37
Exp/Cntr=0.3,0.1

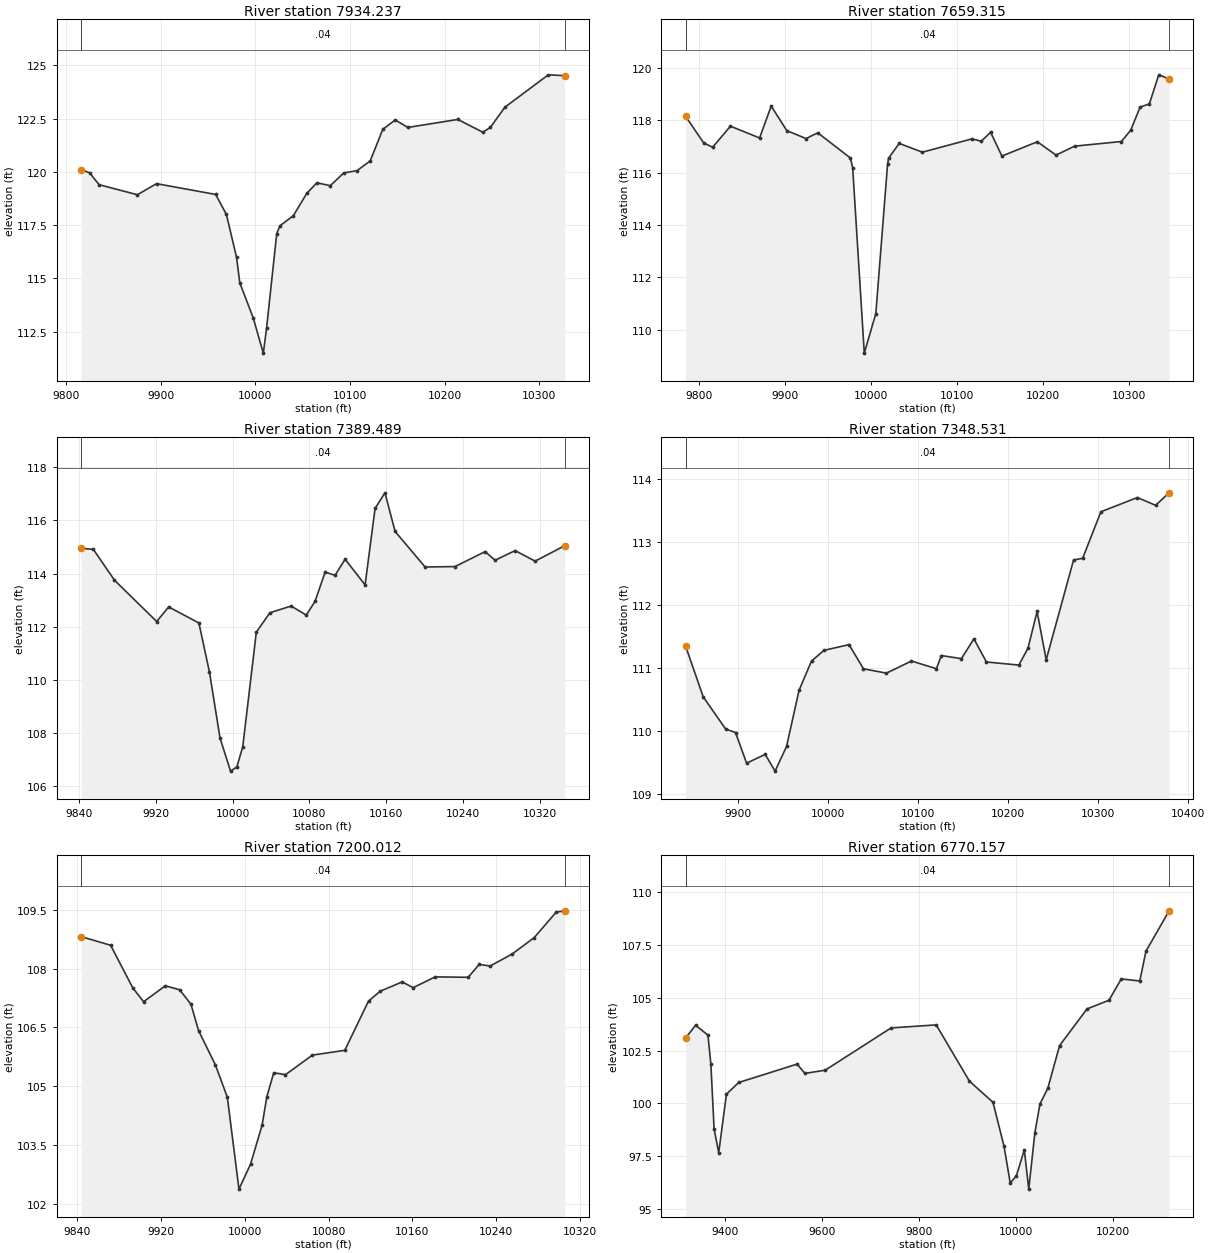
Type RM Length L Ch R = 1 ,7934.237,274.921400,274.921400,274.921400
XS GIS Cut Line= 5
905693.050423819802693.793183318905709.039881522802585.036913836
905694.310773712802546.741233531905587.973968156802440.404427976
905429.553829268802303.685677976
#Sta/Elev= 30
9816.082 120.1019824.969119.95679835.077119.39719875.507118.92519895.722119.4453
9958.189118.9383  9969.5118.00049980.205115.98619983.642114.79269997.784113.1481
10008.49111.491510011.93112.667210022.63117.098610026.07 117.46910040.21117.9411
10054.35118.990410065.06119.4855 10079.2119.351310093.34119.946810107.48120.0577
10121.35120.512510134.56121.991210147.77122.437110160.98122.082710213.81122.4597
10240.23121.859510248.14122.081410263.44123.029110309.36124.553410326.68 124.515
#Mann= 3 , 0 , 0
9816.082    0.04       09816.082    0.04       010326.68    0.04       0
#XS Ineff= 2 , 0
       09933.449                       0
Bank Sta=9816.082,10326.68
Exp/Cntr=0.3,0.1

Type RM Length L Ch R = 1 ,7659.315,269.826100,269.826100,269.826100
XS GIS Cut Line= 4
905844.050357045802505.508594642905824.519107045802433.894011309
905661.758690379 802255.94262242905433.894107045 802158.28637242
#Sta/Elev= 30
9783.916118.16359805.173117.13649815.539116.97629836.269117.78069870.199117.3305
9883.751118.54889901.884 117.6119924.407117.30789937.959117.52729975.968 116.565
9978.615116.19639992.167109.1087 10005.6110.621810019.27116.320810020.42116.5563
10032.82 117.12210059.93116.787310117.54117.295910128.42117.2053 10139.3117.5477
10152.47116.6387 10193.7117.185110215.45116.676410237.21117.017610291.61117.1954
10302.49117.626110313.37118.506710324.25118.634210335.13119.743110347.21119.5866
#Mann= 3 , 0 , 0
9783.916    0.04       09783.916    0.04       010347.21    0.04       0
#XS Ineff= 2 , 0
       09812.567                       0
Bank Sta=9783.916,10347.21
Exp/Cntr=0.3,0.1

Type RM Length L Ch R = 1 ,7389.489,40.957700,40.957700,40.957700
XS GIS Cut Line= 4
905942.996692965802256.656979272905876.050527551802110.425431814
905823.776797856802058.151702119905565.404523712801982.071094643
#Sta/Elev= 30
 9842.15114.95019854.971114.90599876.967113.7473 9920.96112.19479933.431112.7442
9964.952112.1391 9975.95110.29389986.948107.81549997.947106.568710004.46106.7239
10010.65  107.4810024.79111.791210038.93112.523610061.03112.7769 10076.9112.4363
10086.05112.955610096.48114.0504 10106.9113.932910117.33 114.53710138.18113.5721
 10148.6116.447210158.87117.033810169.45115.581310200.72114.2445   10232 114.261
10263.27114.823510273.69 114.49810294.54114.861610315.39114.465510346.24115.0452
#Mann= 3 , 0 , 0
 9842.15    0.04       0 9842.15    0.04       010346.24    0.04       0
#XS Ineff= 2 , 0
       0 9962.75        10042.07       0
Bank Sta=9842.15,10346.24
Exp/Cntr=0.3,0.1

Type RM Length L Ch R = 1 ,7348.531,148.518900,148.518900,148.518900
XS GIS Cut Line= 4
905993.156990618 802225.53789939905950.085441381 802131.11181064
905766.093326449801939.818421334905600.182394415801913.142881021
#Sta/Elev= 30
9841.539111.35249861.194110.53979886.095110.02869897.086109.97239909.386109.4852
 9930.06109.62419941.051109.35829953.804109.75189967.679110.64419981.511111.1102
9995.429111.279910023.18111.371110039.21110.9867 10064.8110.917110092.55111.1098
 10120.3110.987910125.77111.197110148.05111.147610161.93111.4636 10175.8111.0947
10211.85111.045610221.98111.313310232.11 111.89810242.23111.128610272.62112.7169
10282.75112.7449   10303113.484810343.52113.710910363.78113.587210378.78 113.786
#Mann= 3 , 0 , 0
9841.539    0.04       09841.539    0.04       010378.78    0.04       0
#XS Ineff= 2 , 0
       09953.835         10073.4       0
Bank Sta=9841.539,10378.78
Exp/Cntr=0.3,0.1

Type RM Length L Ch R = 1 ,7200.012,429.855500,429.855500,429.855500
XS GIS Cut Line= 6
906120.092023712802101.862761309 906101.79592663 802044.77237715
906063.813269222 802017.93510642906037.836388938802002.686178328
905907.185890444801935.582450174905737.279523712801880.508594643
#Sta/Elev= 30
9843.518108.82029871.727108.5983 9892.97107.5078 9903.23107.15769924.034107.5646
9937.733107.46149948.523107.09119955.774106.41849971.791105.54749983.251104.7206
9994.367102.372910005.44103.011310016.53104.008610020.95104.726410027.61 105.344
 10038.8105.294510064.55105.794410095.48105.915710118.15 107.173 10129.3107.4246
10150.33 107.66310160.84107.516310181.87107.7919 10213.4107.780710223.91108.1092
10234.43 108.06910255.45108.375610276.48108.7935 10297.5109.443810305.62109.4777
#Mann= 3 , 0 , 0
9843.518    0.04       09843.518    0.04       010305.62    0.04       0
#XS Ineff= 2 , 0
       0                               0
Bank Sta=9843.518,10305.62
Exp/Cntr=0.3,0.1

Type RM Length L Ch R = 1 ,6770.157,373.066900,373.066900,373.066900
XS GIS Cut Line= 2
906427.383690379802151.341927976905810.196190379801367.487761309
#Sta/Elev= 30
9318.992103.08789339.792103.69699365.247103.2297 9371.34101.85379377.975 98.7998
9387.50497.671229403.431 100.4419428.886 100.9929549.152101.86049565.317101.4219
9607.075101.5713 9743.13103.57119836.175103.71329904.778101.05329953.272100.0563
 9976.1897.969859988.90896.2361210001.6496.5835810017.9397.8092310027.0995.95134
10039.8298.6268810050.2699.9768910066.43100.718710090.73102.737110147.25104.4677
10192.55104.877610218.01105.884910256.19105.790710268.92107.198610316.66109.1048
#Mann= 3 , 0 , 0
9318.992    0.04       09318.992    0.04       010316.66    0.04       0
#XS Ineff= 2 , 0
       09754.307                       0
Bank Sta=9318.992,10316.66
Exp/Cntr=0.3,0.1

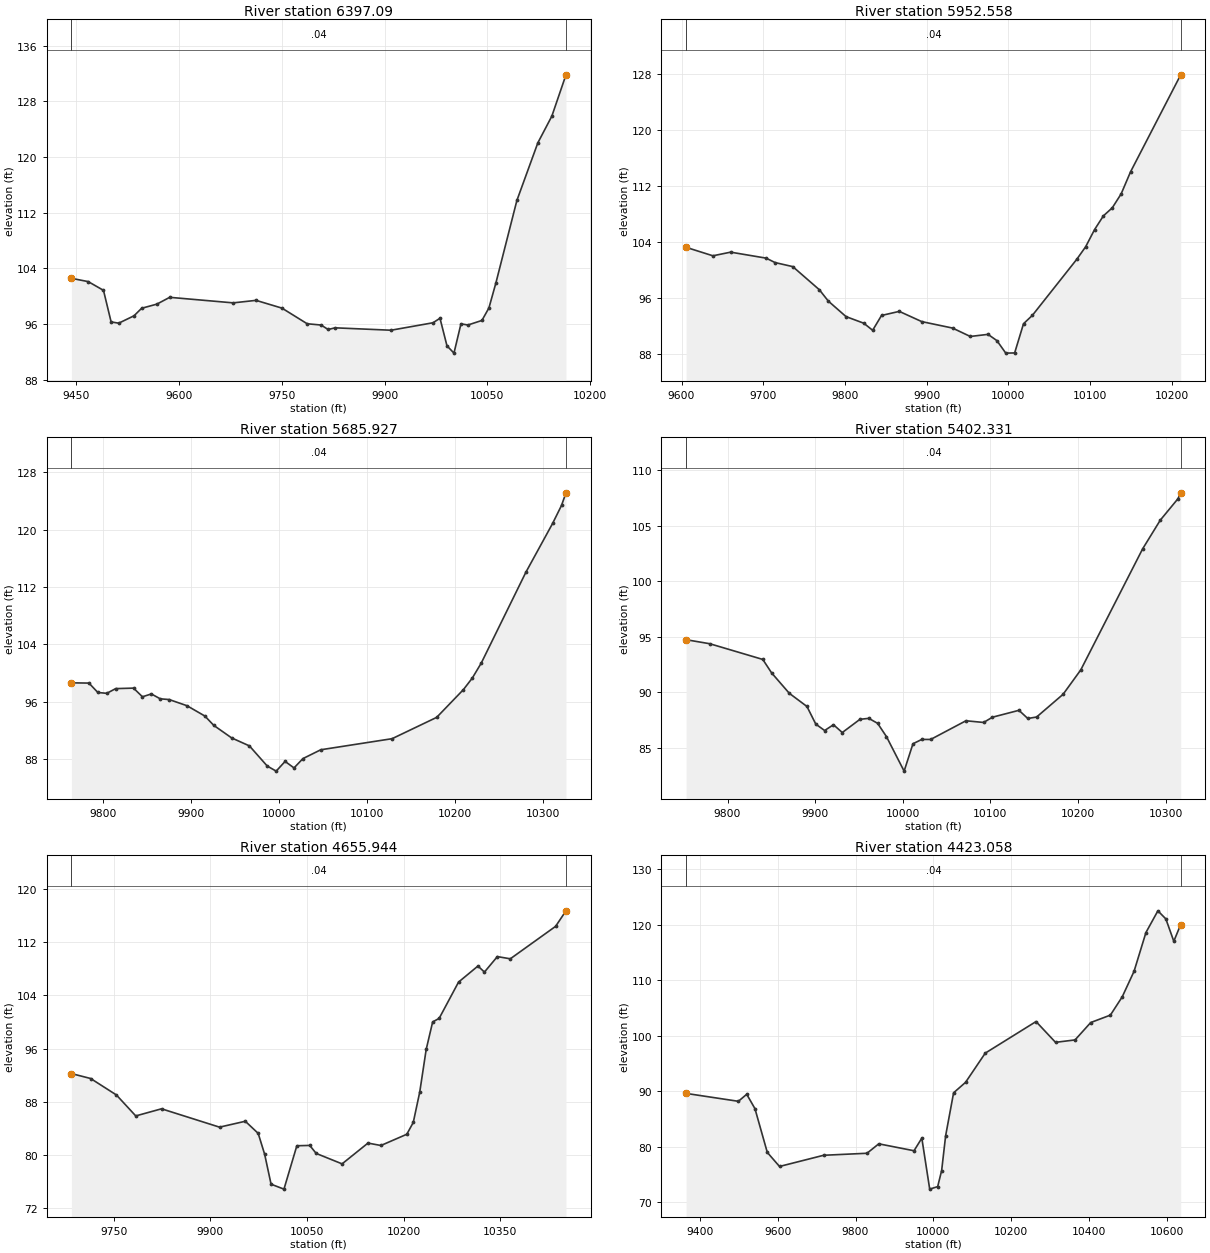
Type RM Length L Ch R = 1 , 6397.09,444.531900,444.531900,444.531900
XS GIS Cut Line= 3
906448.217023712802107.071094643906312.800357045801831.029427976
906396.133690379801424.779427976
#Sta/Elev= 30
9442.644102.54879467.228102.07189489.505100.81839500.64396.277789511.78296.10087
9534.05997.158779545.19798.240499567.47498.837499586.18199.814769678.85999.01876
9712.27499.378499750.11298.262069786.89296.017769807.30895.829969817.517  95.192
9827.72595.431619909.39195.08603 9970.6496.158839980.84896.804839991.05692.84614
10001.2691.7946710011.47 96.001110021.6895.83906 10042.196.4914110052.3198.28836
10062.51101.888210093.14113.736410123.76122.023410144.18125.853410164.82131.7932
#Mann= 3 , 0 , 0
9442.644    0.04       09442.644    0.04       010164.82    0.04       0
#XS Ineff= 2 , 0
       09931.323                       0
Bank Sta=9442.644,10164.82
Exp/Cntr=0.3,0.1

Type RM Length L Ch R = 1 ,5952.558,266.631500,266.631500,266.631500
XS GIS Cut Line= 2
906482.071190379802185.196094643906719.050357045801627.904427976
#Sta/Elev= 30
9605.599103.21919638.412102.01019660.145102.52999703.612101.67469714.478101.0443
9736.211100.46399768.81197.153019779.67895.542749801.41193.321589823.14492.37757
 9834.0191.366069844.877 93.4843 9866.6194.069219894.18292.60551 9931.8191.68561
9953.543 90.48459975.27690.784919986.14289.890699997.00988.1036910007.8888.13131
10018.7492.3044710029.61 93.503810083.94  101.5110094.81103.299310105.67105.7407
10116.54107.714910127.41108.864110138.27110.852110149.73113.992710211.18 127.865
#Mann= 3 , 0 , 0
9605.599    0.04       09605.599    0.04       010211.18    0.04       0
#XS Ineff= 2 , 0
       09856.274                       0
Bank Sta=9605.599,10211.18
Exp/Cntr=0.3,0.1

Type RM Length L Ch R = 1 ,5685.927,283.595300,283.595300,283.595300
XS GIS Cut Line= 2
906742.487857045802234.675261309906833.633690379801679.987761309
#Sta/Elev= 30
9763.60998.653099783.54898.618949793.68297.310259803.81797.193299813.95197.84735
9834.21997.917669844.353 96.71099854.48797.107319864.62196.426719874.75596.32669
9895.02395.465739915.29294.031659925.42692.732299945.69490.987129965.96289.87073
 9986.2387.063959996.36586.35913 10006.587.7118310016.63 86.806210026.7788.10465
10047.0489.3332810128.1190.8757810178.7893.8448110209.1897.7123510219.3199.32495
10229.45101.405110280.12114.041710310.52120.842810320.66123.353210325.74125.1109
#Mann= 3 , 0 , 0
9763.609    0.04       09763.609    0.04       010325.74    0.04       0
#XS Ineff= 2 , 0
       0                               0
Bank Sta=9763.609,10325.74
Exp/Cntr=0.3,0.1

Type RM Length L Ch R = 1 ,5402.331,746.387200,746.387200,746.387200
XS GIS Cut Line= 2
907004.263461948802291.813741538907077.180128615801731.917908204
#Sta/Elev= 30
9752.69594.742649779.73594.379379840.24292.964159850.327 91.75089870.49689.91433
9890.66488.726489900.74987.136349910.83386.560639920.91887.082279931.00286.37907
9951.17187.570129961.25687.65675 9971.3487.207539981.42486.0101310001.5982.90206
10011.6885.3685810021.7685.7580710031.8585.7546610072.1887.4391610092.3587.28663
10102.4487.7608210132.69 88.381210142.7887.6435110152.8687.7776910183.1189.82797
10203.2892.0250710273.87102.926310294.04105.514710314.21107.443110317.32107.9751
#Mann= 3 , 0 , 0
9752.695    0.04       09752.695    0.04       010317.32    0.04       0
#XS Ineff= 2 , 0
       0                               0
Bank Sta=9752.695,10317.32
Exp/Cntr=0.3,0.1

Type RM Length L Ch R = 1 ,4655.944,232.885800,232.885800,232.885800
XS GIS Cut Line= 3
907489.291298844802524.877045281907492.904096864802156.371647171
907456.776116657801758.963864895
#Sta/Elev= 30
9684.20892.242059714.08691.501719754.08889.02901 9784.0985.885659824.09286.95384
9914.09684.199719954.09885.084359974.09983.268219984.09980.14364  9994.175.63832
 10014.174.89782 10034.181.4079910054.1181.4563810064.1580.2543110104.3178.68952
10144.4881.8092210164.5681.4468310204.73 83.131910214.7784.9046810224.8189.45845
10234.8595.8722910244.8999.9975510254.93100.522710285.06105.972710315.18108.3831
10325.22107.4739 10345.3109.799810365.39 109.46810435.68114.338610451.78116.6689
#Mann= 3 , 0 , 0
9684.208    0.04       09684.208    0.04       010451.78    0.04       0
#XS Ineff= 2 , 0
       09959.331                       0
Bank Sta=9684.208,10451.78
Exp/Cntr=0.3,0.1

Type RM Length L Ch R = 1 ,4423.058,396.000000,396.000000,396.000000
XS GIS Cut Line= 6
907794.976754672802718.752480975907700.691925499802467.329002206
907654.317395775802201.581525121907692.326268654801830.073503852
907677.882594818801672.870466049907640.273119215801477.709324794
#Sta/Elev= 30
9364.65389.634649498.937  88.2139520.39989.480129541.53486.887239573.23579.00852
9604.61876.473819717.98578.489479829.428 78.85259859.68780.552749950.19579.30482
9970.259 81.57499990.50772.3915710010.9972.8446110021.2275.7461210031.4582.01509
 10051.989.7462310082.5891.6256810133.2496.8906310263.68102.577310313.7498.83574
 10363.999.2682910404.19102.401410454.68103.736510485.13107.029210515.58  111.64
10546.07118.618310576.75122.5251 10597.2121.070110617.65117.043110635.33120.0504
#Mann= 3 , 0 , 0
9364.653    0.04       09364.653    0.04       010635.33    0.04       0
#XS Ineff= 2 , 0
       09866.253                       0
Bank Sta=9364.653,10635.33
Exp/Cntr=0.3,0.1

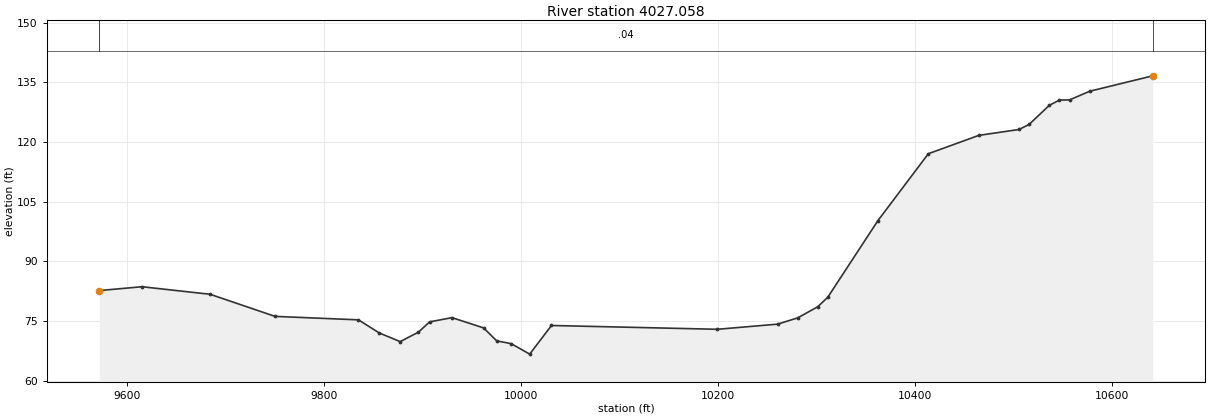
Type RM Length L Ch R = 1 ,4027.058,0.000000,0.000000,0.000000
XS GIS Cut Line= 6
908171.557648904802558.921344775908121.170753727802436.858703302
907991.771480347802182.013578229907948.789423134 802084.85241089
 907929.74249834 802013.67738713907834.273759985801552.467247839
#Sta/Elev= 30
9572.29882.636469615.69383.594529684.72681.69536 9750.6476.141629835.24975.27159
9856.41771.968919877.58569.801229896.10372.171129907.44974.756819930.14175.82381
9962.256 73.24669975.52469.989449990.25869.2894910009.0266.65341 10031.173.85408
10199.4872.89749 10260.674.1902210280.9775.7649410301.3478.5665410311.5380.96176
10362.46100.238510413.55117.027810464.72 121.63810505.66123.128910515.89124.4089
10536.36129.205410546.59 130.51810556.82130.554410577.29132.737210641.28136.6131
#Mann= 3 , 0 , 0
9572.298    0.04       09572.298    0.04       010641.28    0.04       0
#XS Ineff= 2 , 0
       09926.273                       0
Bank Sta=9572.298,10641.28
Exp/Cntr=0.3,0.1